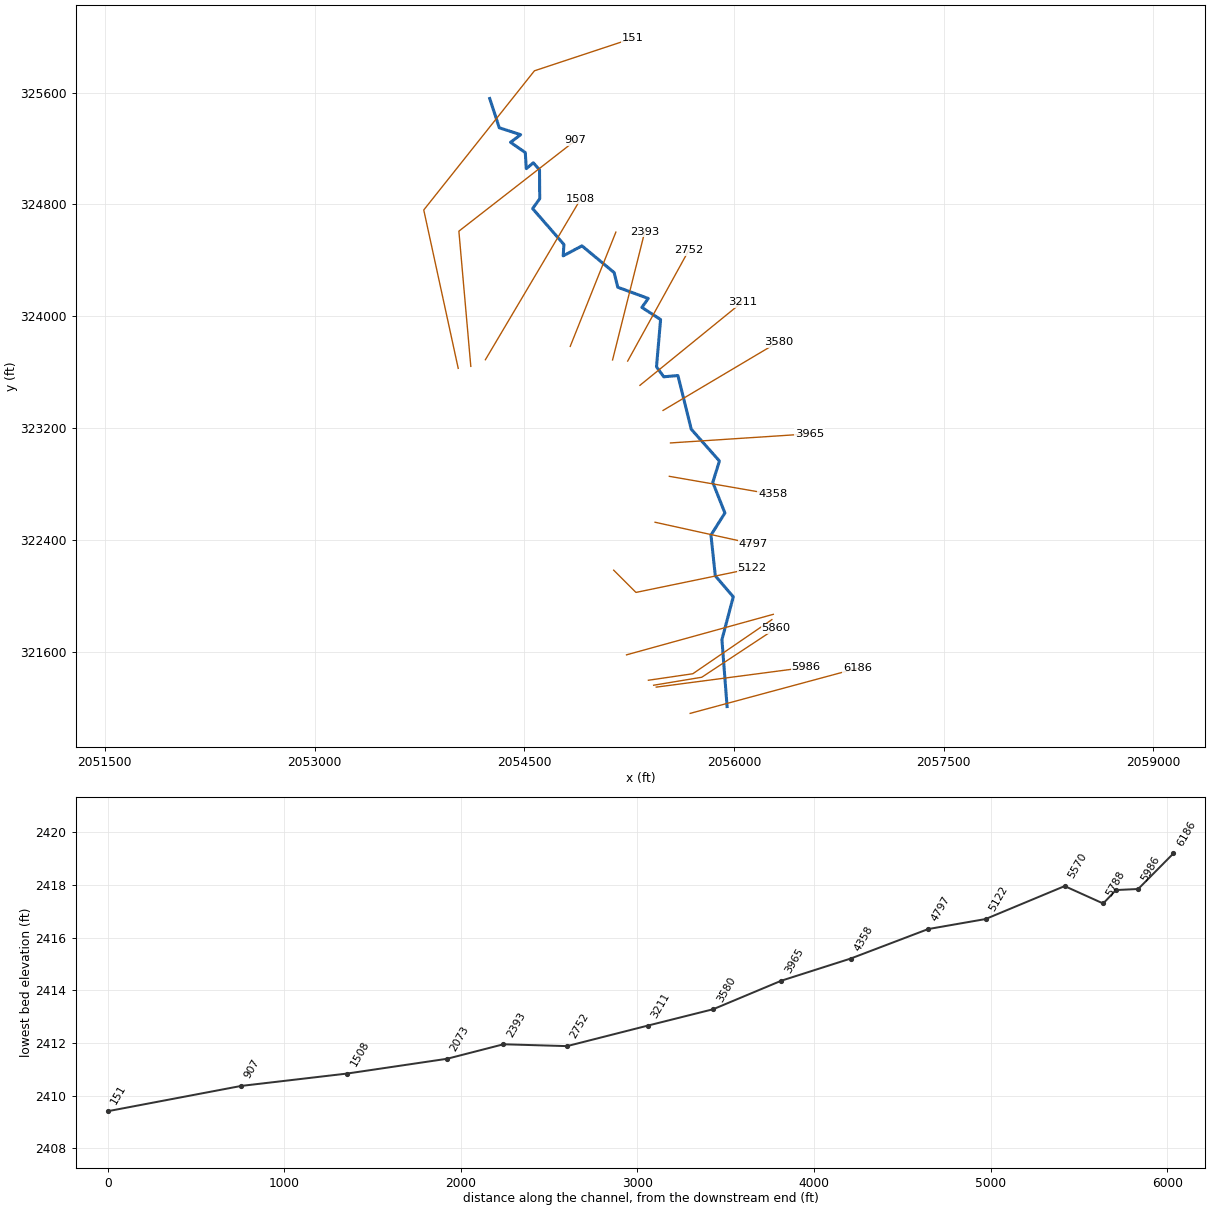
--- CALLAHNBR.prj (project) ---

Proj Title=CALLAHNBR
Current Plan=p01
Default Exp/Contr=0.3,0.1
English Units
Geom File=g01
Flow File=f01
Plan File=p01
Y Axis Title=Elevation
X Axis Title(PF)=Main Channel Distance
X Axis Title(XS)=Station
BEGIN DESCRIPTION:
Stream Name- Callahan Branch
Flood Zone: Zone A
Greenbrier County, WV
County-Wide Study
WVDHSEM-2018-3, Flood Risk Project
HEC-RAS Version: 5.0.7
General Notes:
For the Hydrology regression was used.
END DESCRIPTION:
DSS File=dss
DSS Export Rating Curves= 0
DSS Export Rating Curve Sorted= 0
DSS Export Volume Flow Curves= 0
DXF Filename=..\H2c.
DXF OffsetX= 0
DXF OffsetY= 0
DXF ScaleX= 1
DXF ScaleY= 10

--- CALLAHNBR.p01 (plan) ---

Plan Title=Floodplain
Program Version=5.07
Short Identifier=Floodplain
Geom File=g01
Flow File=f01
Subcritical Flow
K Sum by GR= 0
Std Step Tol= 0.01
Critical Tol= 0.01
Num of Std Step Trials= 20
Max Error Tol= 0.3
Flow Tol Ratio= 0.001
Split Flow NTrial= 30
Split Flow Tol= 0.02
Split Flow Ratio= 0.02
Log Output Level= 0
Friction Slope Method= 1
Unsteady Friction Slope Method= 2
Unsteady Bridges Friction Slope Method= 1
Parabolic Critical Depth
Global Vel Dist= 0 , 0 , 0
Global Log Level= 0
CheckData=True
Encroach Param=-1 ,0,0, 0
Computation Interval=1MIN
Output Interval=1HOUR
Instantaneous Interval=1HOUR
Mapping Interval=1HOUR
Computation Time Step Use Courant=        0
Computation Time Step Use Time Series=    0
Computation Time Step Count To Double=0
Computation Time Step Max Doubling=0
Computation Time Step Max Halving=0
Computation Time Step Residence Courant=0
Run HTab= 0
Run UNet= 0
Run Sediment= 0
Run PostProcess= 0
Run WQNet= 0
Run RASMapper=-1
UNET Theta= 1
UNET Theta Warmup= 1
UNET ZTol= 0.02
UNET ZSATol= 0.02
UNET MxIter= 20
UNET Max Iter WO Improvement= 0
UNET MaxInSteps= 0
UNET DtIC= 0
UNET DtMin= 0
UNET MaxCRTS= 20
UNET WFStab= 2
UNET SFStab= 1
UNET WFX= 1
UNET SFX= 1
UNET 1D Methodology=Finite Difference
UNET DSS MLevel= 4
UNET Pardiso=0
UNET DZMax Abort= 100
UNET Use Existing IB Tables=-1
UNET Froude Reduction=False
UNET Froude Limit= 0.8
UNET Froude Power= 4
UNET D1 Cores= 0
UNET D2 Coriolis=0
UNET D2 Cores= 0
UNET D2 Theta= 1
UNET D2 Theta Warmup= 1
UNET D2 Z Tol= 0.01
UNET D2 Volume Tol= 0.01
UNET D2 Max Iterations= 20
UNET D2 Equation= 0
UNET D2 RampUpFraction=0.1
UNET D2 TimeSlices= 1
UNET D2 BCVolumeCheck=0
UNET D1D2 MaxIter= 0
UNET D1D2 ZTol=0.01
UNET D1D2 QTol=0.1
UNET D1D2 MinQTol=1
DSS File=dss
Write IC File= 0
Write IC File at Fixed DateTime=0
Write IC File at Sim End=0
Echo Input=False
Echo Parameters=False
Echo Output=False
Write Detailed= 0
HDF Write Warmup=0
HDF Write Time Slices=0
HDF Flush=0
HDF Face Node Velocities=0
HDF Compression= 1
HDF Chunk Size= 1
HDF Spatial Parts= 1
HDF Use Max Rows=0
HDF Fixed Rows= 1
Calibration Method= 0
Calibration Iterations= 20
Calibration Max Change=0.05
Calibration Tolerance=0.2
Calibration Maximum=1.5
Calibration Minimum=0.5
Calibration Optimization Method= 1
WQ AD Non Conservative
WQ ULTIMATE=-1
WQ Max Comp Step=1HOUR
WQ Output Interval=15MIN
WQ Output Selected Increments= 0
WQ Output face flow=0
WQ Output face velocity=0
WQ Output face area=0
WQ Output face dispersion=0
WQ Output cell volume=0
WQ Output cell surface area=0
WQ Output cell continuity=0
WQ Output cumulative cell continuity=0
WQ Output face conc=0
WQ Output face dconc_dx=0
WQ Output face courant=0
WQ Output face peclet=0
WQ Output face adv mass=0
WQ Output face disp mass=0
WQ Output cell mass=0
WQ Output cell source sink temp=0
WQ Output nsm pathways=0
WQ Output nsm derived pathways=0
WQ Output MaxMinRange=-1
WQ Daily Max Min Mean=-1
WQ Daily Range=0
WQ Daily Time=0
WQ Create Restart=0
WQ Fixed Restart=0
WQ System Summary=0
WQ Write To DSS=0
WQ Use Fixed Temperature=0
Sorting and Armoring Iterations= 10
XS Update Threshold= 0.02
Bed Roughness Predictor= 0
Hydraulics Update Threshold= 0.02
Energy Slope Method= 1
Volume Change Method= 1
Sediment Retention Method= 0
XS Weighting Method= 0
Number of US Weighted Cross Sections= 1
Number of DS Weighted Cross Sections= 1
Upstream XS Weight=0
Main XS Weight=1
Downstream XS Weight=0
Number of DS XS's Weighted with US Boundary= 1
Upstream Boundary Weight= 1
Weight of XSs Associated with US Boundary= 0
Number of US XS's Weighted with DS Boundary= 1
Downstream Boundary Weight= 0.5
Weight of XSs Associated with DS Boundary= 0.5
Percentile Method= 0
Sediment Output Level= 3
Mass or Volume Output= 0
Output Increment Type= 1
Profile and TS Output Increment= 1
XS Output Flag= 0
XS Output Increment= 10
Write Gradation File= 0
Read Gradation Hotstart= 0
Write HDF5 File= 1
Write Binary Output= 1
Write DSS Sediment File= 0
SV Curve= 0
Specific Gage Flag= 0

--- CALLAHNBR.f01 (steady flow) ---

Flow Title=H2c
Program Version=5.07
Number of Profiles= 6
Profile Names=f1p,f10p,f4p,f2p,f02p,f1pplus
River Rch & RM=CALLAHNBR,Main            ,6186
     480     252     336     406     672     710
River Rch & RM=CALLAHNBR,Main            ,5986
     542     286     381     459     759     802
River Rch & RM=CALLAHNBR,Main            ,3580
     612     324     431     519     854     906
Boundary for River Rch & Prof#=CALLAHNBR,Main            , 1
Up Type= 0
Dn Type= 3
Dn Slope=0.00105
Boundary for River Rch & Prof#=CALLAHNBR,Main            , 2
Up Type= 0
Dn Type= 3
Dn Slope=0.00105
Boundary for River Rch & Prof#=CALLAHNBR,Main            , 3
Up Type= 0
Dn Type= 3
Dn Slope=0.00105
Boundary for River Rch & Prof#=CALLAHNBR,Main            , 4
Up Type= 0
Dn Type= 3
Dn Slope=0.00105
Boundary for River Rch & Prof#=CALLAHNBR,Main            , 5
Up Type= 0
Dn Type= 3
Dn Slope=0.00105
Boundary for River Rch & Prof#=CALLAHNBR,Main            , 6
Up Type= 0
Dn Type= 3
Dn Slope=0.00105
DSS Import GetInterval= 0
DSS Import GetPeak= 0
DSS Import FillOption= 0

--- CALLAHNBR.g01 (geometry) ---

Geom Title=H2c
Program Version=5.07

River Reach=CALLAHNBR       ,Main
Reach XY= 30
     2055951.231      321208.142     2055914.307      321686.695
2055995.31568651321993.0899780672055866.89233104322143.288824246
     2055835.871      322434.6272055935.60442632 322592.82831034
     2055848.812      322811.643     2055896.403      322964.831
     2055694.935      323191.9142055599.57967711323576.092082198
     2055498.114      323566.978     2055446.275      323638.516
2055475.53985015323976.412716616     2055341.945      324063.302
     2055387.048      324127.598     2055169.188      324207.518
     2055143.195      324312.598     2054913.198      324503.592
     2054778.868      324432.2572054784.11261393324513.453073434
     2054560.111      324770.271     2054610.984      324840.826
     2054609.451      325047.515     2054565.053       325097.74
     2054514.941      325055.881      2054507.69      325171.037
     2054402.068      325244.403     2054474.765      325298.776
     2054321.754      325348.215     2054253.284      325557.514

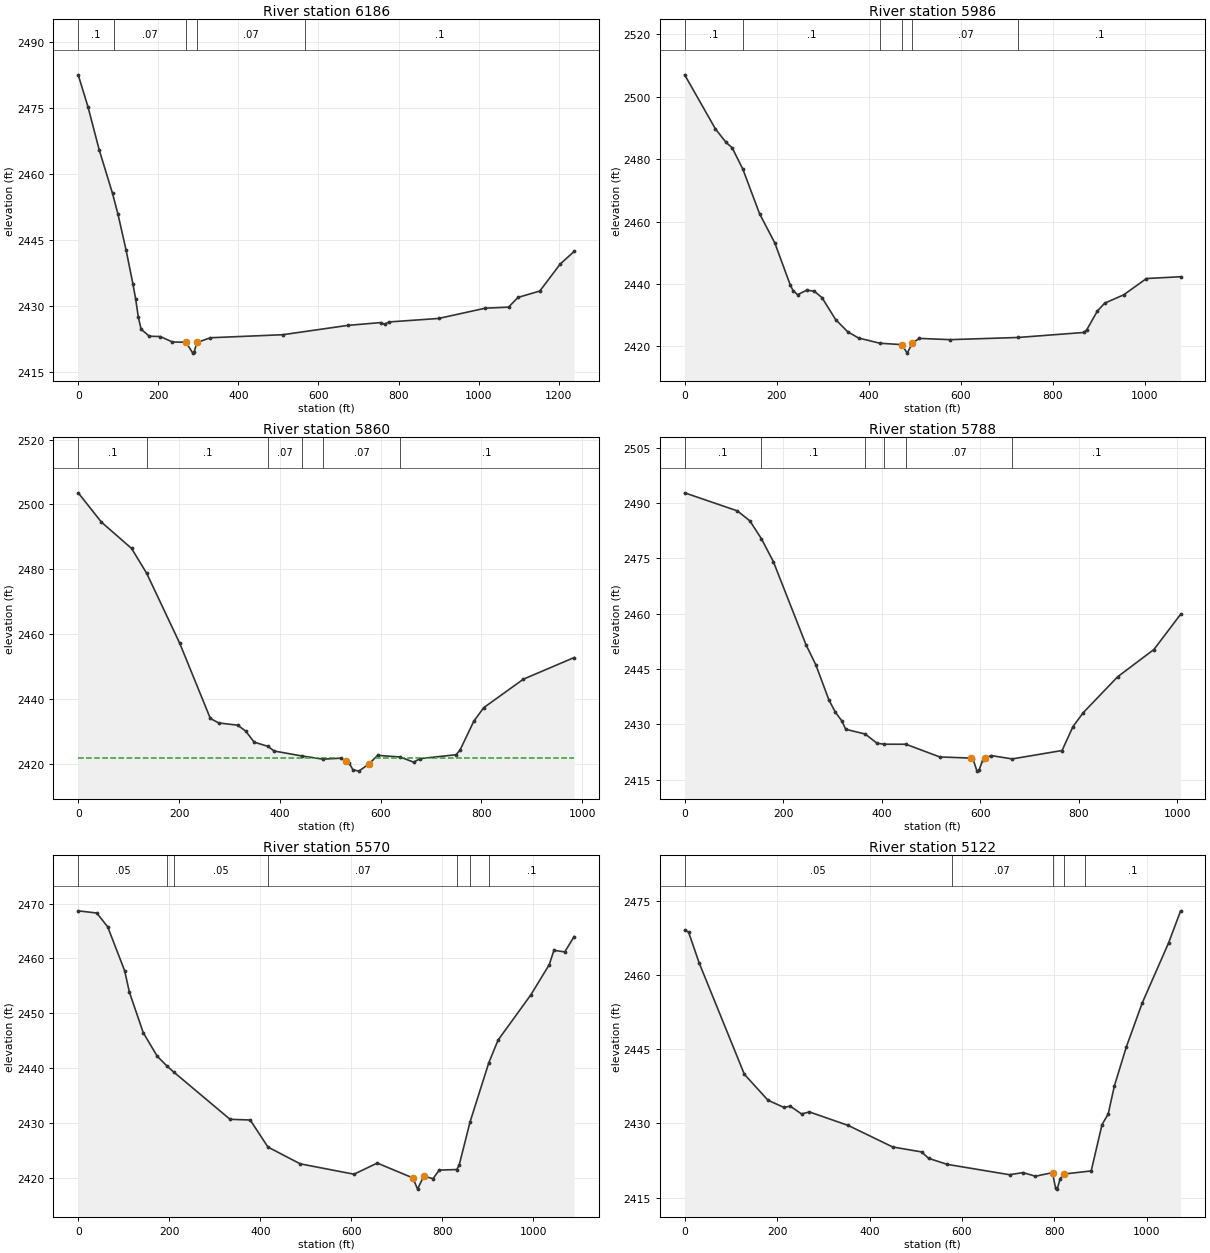
Type RM Length L Ch R = 1 ,6186    ,197.5,199.6,196.1
XS GIS Cut Line= 2
2055687.05941715321159.4692225122056882.79580169321481.869135067
#Sta/Elev= 30
       0 2482.51    24.5 2475.19    52.5 2465.41    85.7 2455.52    99.3 2450.79
   119.4  2442.7   136.6 2434.93   143.5 2431.48   150.2 2427.31     157 2424.64
   177.4 2423.04   205.1 2422.96   235.2 2421.73   269.2 2421.66   286.1 2419.19
   289.5 2419.45   296.3 2421.61   330.3 2422.69   510.8 2423.38   673.1  2425.5
   755.1 2426.14   765.3 2425.75   775.5 2426.28     900 2427.08  1016.7 2429.42
  1074.5 2429.65  1098.3 2431.87  1152.6 2433.32  1203.6 2439.46  1238.4 2442.33
#Mann= 5 ,-1 , 0
       0      .1       0   88.31     .07       0   269.2    .045       0
   296.3     .07       0  565.29      .1       0
Bank Sta=269.2,296.3
XS Rating Curve= 0 ,0
Exp/Cntr(USF)=0,0
Exp/Cntr=0.3,0.1

Type RM Length L Ch R = 1 ,5986    ,110.4,125.9,135.5
XS GIS Cut Line= 2
2055444.23922984321347.195753873 2056513.4642563321487.990652394
#Sta/Elev= 30
       0 2507.02    66.9 2489.68    90.1 2485.34   103.3 2483.64   126.5 2476.79
   162.9  2462.5     196 2453.15   229.3 2439.81   235.7 2437.86   245.6 2436.56
   265.5 2438.02     282 2437.67   298.6 2435.62   328.3 2428.59   354.5 2424.69
     378 2422.69   424.3 2421.02     472 2420.56   483.9 2417.84   495.4 2421.11
   510.3 2422.56   577.3 2422.16   725.4 2422.86   867.7 2424.46   874.3  2425.3
   897.5 2431.34   913.5 2433.87   954.5  2436.5  1004.2 2441.75  1078.5 2442.32
#Mann= 6 ,-1 , 0
       0      .1       0   126.5      .1       0   424.3     .07       0
     472    .045       0   495.4     .07       0   725.4      .1       0
Bank Sta=472,495.4
XS Rating Curve= 0 ,0
Exp/Cntr(USF)=0,0
Exp/Cntr=0.5,0.3

Type RM Length L Ch R = 1 ,5860    ,78.5,72.3,66.9
XS GIS Cut Line= 3
2055425.78149229321360.7908773962055770.16097094321417.890065567
2056300.11281115321767.622593114
#Sta/Elev= 30
       0 2503.59      46 2494.57   105.9 2486.44   135.8  2478.8   201.6 2457.15
   262.2 2434.03   278.8 2432.65   316.3 2431.96   332.1 2430.18   349.1 2426.74
   376.4 2425.44   388.7    2424     445 2422.44   485.3  2421.5   521.6 2421.79
   530.82420.826   537.3 2420.33   545.1 2418.23   556.9  2417.8   576.9 2420.04
   594.2 2422.66   638.8 2422.15   665.3 2420.58   678.8 2421.65   749.6 2422.86
   757.4 2424.24   784.9 2433.19   804.6 2437.36   883.2 2446.14     984 2452.81
#Mann= 6 ,-1 , 0
       0      .1       0   135.8      .1       0   376.4     .07       0
     445    .045       0   485.3     .07       0   638.8      .1       0
#XS Ineff= 2 , 0
          517.09    2422  588.36            2422
Permanent Ineff=
       F       F
Bank Sta=530.8,576.9
XS Rating Curve= 0 ,0
Exp/Cntr(USF)=0,0
Exp/Cntr=0.5,0.3

Type RM Length L Ch R = 1 ,5788    ,218.9,218.2,204.8
XS GIS Cut Line= 3
2055388.31015005321396.4778700032055705.92438425321442.870960392
2056271.56321707321830.074830176
#Sta/Elev= 30
       0 2492.73     107 2487.83   132.4 2485.11   155.7 2480.29   179.9 2474.11
   246.2 2451.56   266.1 2446.13   292.7 2436.59   305.9 2433.24   318.8 2430.95
   326.8 2428.63   366.5 2427.34   390.4 2424.84   404.7 2424.59   448.9 2424.58
   517.6 2421.14   581.2 2420.82   585.2 2420.57   593.2 2417.29   597.1  2417.5
   605.1 2420.32   609.1 2420.78   621.9 2421.51   664.7  2420.6   765.9 2422.88
     788 2429.36     809 2433.16   878.7 2442.87   952.3 2450.26  1006.5 2459.81
#Mann= 6 ,-1 , 0
       0      .1       0   155.7      .1       0   366.5     .07       0
   404.7    .045       0   448.9     .07       0   664.7      .1       0
Bank Sta=581.2,609.1
XS Rating Curve= 0 ,0
Exp/Cntr(USF)=0,0
Exp/Cntr=0.5,0.3

Type RM Length L Ch R = 1 ,5570    ,441.4,448,439.5
XS GIS Cut Line= 2
2055231.71000682321578.1034266272056281.84903003321868.029865727
#Sta/Elev= 30
       0 2468.68    40.8 2468.28    64.7 2465.77   102.1 2457.74   112.3 2453.89
   142.9 2446.46   173.6 2442.17   194.9  2440.4   210.2 2439.27   333.5 2430.68
   377.8 2430.55   416.8 2425.62   487.6 2422.56   605.8 2420.67   656.9  2422.7
   735.2 2419.99   745.4 2417.95     759 2420.32   779.4 2419.86     793 2421.42
   831.7 2421.52     837 2422.39   860.7 2430.19   901.9 2440.99   922.3 2445.12
   994.4 2453.38  1034.7 2458.87    1045 2461.49  1068.7 2461.19  1089.4 2463.99
#Mann= 7 ,-1 , 0
       0     .05       0   194.9     .07       0   210.2     .05       0
   416.8     .07       0   831.7      .1       0   860.7    .045       0
   901.9      .1       0
Bank Sta=735.2,759
XS Rating Curve= 0 ,0
Exp/Cntr(USF)=0,0
Exp/Cntr=0.3,0.1

Type RM Length L Ch R = 1 ,5122    ,318.5,324.8,308.1
XS GIS Cut Line= 3
2055140.20386927322183.8031218972055299.36331977322024.643671395
2056129.84917047322196.046156551
#Sta/Elev= 30
       0 2469.19     8.4 2468.78    31.6 2462.47   129.2 2439.96   180.4  2434.7
     215 2433.25   228.1 2433.53   252.8 2431.94   269.9 2432.34   353.7 2429.61
   450.2 2425.24   512.5 2424.24     528 2422.93   568.1 2421.72   702.9 2419.62
   732.2 2420.05     759 2419.31   795.9 2420.05   802.6 2416.86   805.9  2416.7
   812.6 2418.84   820.9 2419.76   879.6 2420.39     903 2429.76   916.4 2431.93
   929.8 2437.62   955.6 2445.51   990.1 2454.44  1047.1  2466.6  1073.1 2473.09
#Mann= 5 ,-1 , 0
       0     .05       0  577.35     .07       0   795.9    .045       0
   820.9     .07       0     866      .1       0
Bank Sta=795.9,820.9
XS Rating Curve= 0 ,0
Exp/Cntr(USF)=0,0
Exp/Cntr=0.3,0.1

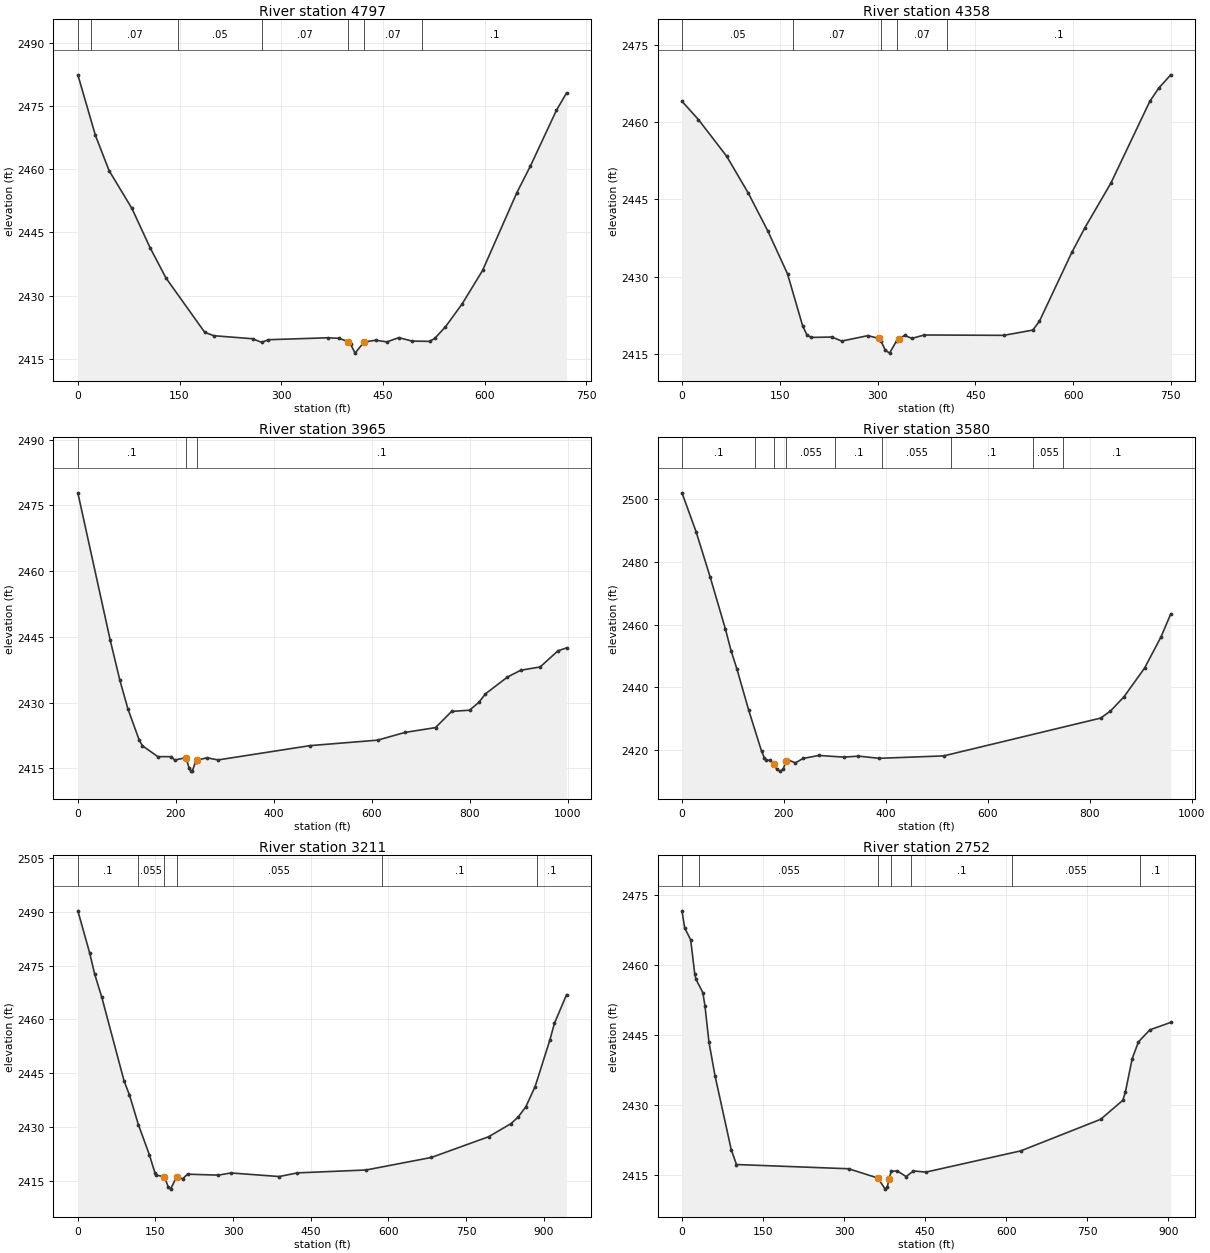
Type RM Length L Ch R = 1 ,4797    ,429,439.4,427.7
XS GIS Cut Line= 2
2055436.07720674 322526.608092212056140.05169935322371.529653259
#Sta/Elev= 30
       0 2482.47    25.9 2468.09    46.1  2459.7    79.8  2450.7   106.5  2441.4
     130 2434.18   187.2 2421.26   200.6 2420.46   257.7 2419.74   271.1 2418.89
   281.2 2419.51   368.9 2419.97   385.4 2419.84   398.8 2419.05   402.2 2418.49
   408.9 2416.32   422.3 2418.99   439.1 2419.38   455.9    2419   473.5    2420
   492.8 2419.19   518.8 2419.11   526.5 2419.83   542.3 2422.59   566.8 2428.01
     597 2435.97   647.4 2454.41   667.6 2460.81     706 2474.06   720.9 2478.17
#Mann= 7 ,-1 , 0
       0      .1       0   19.26     .07       0  148.38     .05       0
  271.61     .07       0   398.8    .045       0   422.3     .07       0
  507.68      .1       0
Bank Sta=398.8,422.3
XS Rating Curve= 0 ,0
Exp/Cntr(USF)=0,0
Exp/Cntr=0.3,0.1

Type RM Length L Ch R = 1 ,4358    ,378,392.5,385.9
XS GIS Cut Line= 2
2055538.10249553322855.1295220922056276.76558632322726.577658225
#Sta/Elev= 30
       0 2464.05    25.3 2460.49    68.6 2453.38   101.9  2446.2   131.9 2438.84
   161.9 2430.58   185.2 2420.45   191.9 2418.69   198.5 2418.25   229.9 2418.32
   245.1 2417.54   285.1 2418.59   301.7 2418.07   305.1 2417.63   311.7 2415.81
   318.4  2415.2   329.1 2417.55   333.4 2417.99   341.7 2418.66   352.6 2418.05
   371.7 2418.72   493.7 2418.65   538.2 2419.67   548.2 2421.34   598.1 2434.74
   618.1 2439.51   658.1  2448.2   717.7 2464.03   731.3 2466.58   749.8 2469.18
#Mann= 5 ,-1 , 0
       0     .05       0  169.81     .07       0   305.1    .045       0
   329.1     .07       0  406.53      .1       0
Bank Sta=301.7,333.4
XS Rating Curve= 0 ,0
Exp/Cntr(USF)=0,0
Exp/Cntr=0.3,0.1

Type RM Length L Ch R = 1 ,3965    ,375.1,385.1,384
XS GIS Cut Line= 2
2055546.26451863323093.8686978452056542.03133715323159.164882667
#Sta/Elev= 30
       0 2477.89    66.2 2444.21    85.9 2435.06   102.3 2428.54   125.3 2421.44
   131.9 2420.15   163.3 2417.67   191.1 2417.66   197.7 2416.87   220.7 2417.46
   227.3 2415.01   230.6 2414.36   233.8 2414.41   240.4 2416.53   243.7 2416.87
   263.4  2417.4   286.4 2416.92   473.9 2420.18   611.9 2421.43   667.8 2423.19
   730.3  2424.3   763.2 2427.99   799.8 2428.27   819.1 2430.09   832.2    2432
   877.2 2435.84   904.6  2437.4     944 2438.14   980.2 2441.82   997.9  2442.5
#Mann= 3 ,-1 , 0
       0      .1       0   220.7    .045       0   243.7      .1       0
Bank Sta=220.7,243.7
XS Rating Curve= 0 ,0
Exp/Cntr(USF)=0,0
Exp/Cntr=0.3,0.1

Type RM Length L Ch R = 1 ,3580    ,357,369.4,358.9
XS GIS Cut Line= 2
2055493.21136846323326.4863562722056317.57570183323816.207742432
#Sta/Elev= 30
       0 2502.09    27.8 2489.62    55.5  2475.1    85.1 2458.68    96.2 2451.77
     108 2445.74   130.9 2432.73   156.1 2419.65   161.4 2417.61   165.2 2416.89
   172.8 2416.69     180 2415.63   185.7 2413.99     192 2413.28   198.5 2413.81
     204 2416.58   207.2 2416.94   222.5 2415.91   237.5 2417.33   268.6 2418.28
   317.9 2417.75   346.3 2418.07   386.5 2417.37   513.3 2418.14   821.5 2430.21
   840.7 2432.46   867.4 2437.04   907.8 2446.22   939.9 2456.13   958.9 2463.42
#Mann= 9 ,-1 , 0
       0      .1       0  142.88    .055       0     180    .045       0
     204    .055       0   300.9      .1       0  393.09    .055       0
  527.44      .1       0  689.49    .055       0  746.65      .1       0
Bank Sta=180,204
XS Rating Curve= 0 ,0
Exp/Cntr(USF)=0,0
Exp/Cntr=0.3,0.1

Type RM Length L Ch R = 1 ,3211    ,442.4,458.3,451.1
XS GIS Cut Line= 2
2055327.93040063323506.050864531 2056060.4719741324101.878551026
#Sta/Elev= 30
       0 2490.26      23 2478.42    32.4 2472.68    46.3 2466.14    89.3 2442.83
    99.7 2438.93     117 2430.63   138.2 2422.24   148.9 2417.21   151.7 2416.57
   167.3 2416.09   174.5 2413.34   179.2 2412.66   190.9 2416.13   202.5 2415.55
   211.9 2416.83   271.3 2416.56   295.8 2417.17   389.1 2416.17   424.1 2417.19
     557    2418     683 2421.49   793.7 2427.27   836.9 2430.93   850.9 2432.78
   865.6 2435.63   883.5 2441.25   912.1 2454.28   920.8 2458.89   944.3 2466.89
#Mann= 6 ,-1 , 0
       0      .1       0  115.31    .055       0   167.3    .045       0
   190.9    .055       0  587.59      .1       0     888      .1       0
Bank Sta=167.3,190.9
XS Rating Curve= 0 ,0
Exp/Cntr(USF)=0,0
Exp/Cntr=0.3,0.1

Type RM Length L Ch R = 1 ,2752    ,348.9,359.8,355.2
XS GIS Cut Line= 2
2055240.18865228323679.4938554622055676.85688827324471.210096422
#Sta/Elev= 30
       0 2471.57     4.9 2467.93    16.1 2465.35    23.6 2458.06    25.9  2456.9
    38.6 2454.01    42.4 2451.26    49.9 2443.41    61.1  2436.2    91.1 2420.36
   100.8 2417.16   308.4 2416.25   362.8 2414.24   375.8 2411.88   379.6 2412.24
   383.3 2414.11   383.3 2414.13   387.1  2415.7   398.3 2415.79   414.7 2414.57
   428.3 2415.78   451.2 2415.53   626.9 2420.09   774.5 2426.85   815.6 2430.93
   820.4 2432.75   832.9 2439.85   844.5 2443.47   865.6 2446.04   904.2 2447.64
#Mann= 7 ,-1 , 0
       0      .1       0   32.32    .055       0   362.8    .045       0
   387.1    .055       0  423.64      .1       0  610.31    .055       0
     847      .1       0
Bank Sta=362.8,383.3
XS Rating Curve= 0 ,0
Exp/Cntr(USF)=0,0
Exp/Cntr=0.3,0.1

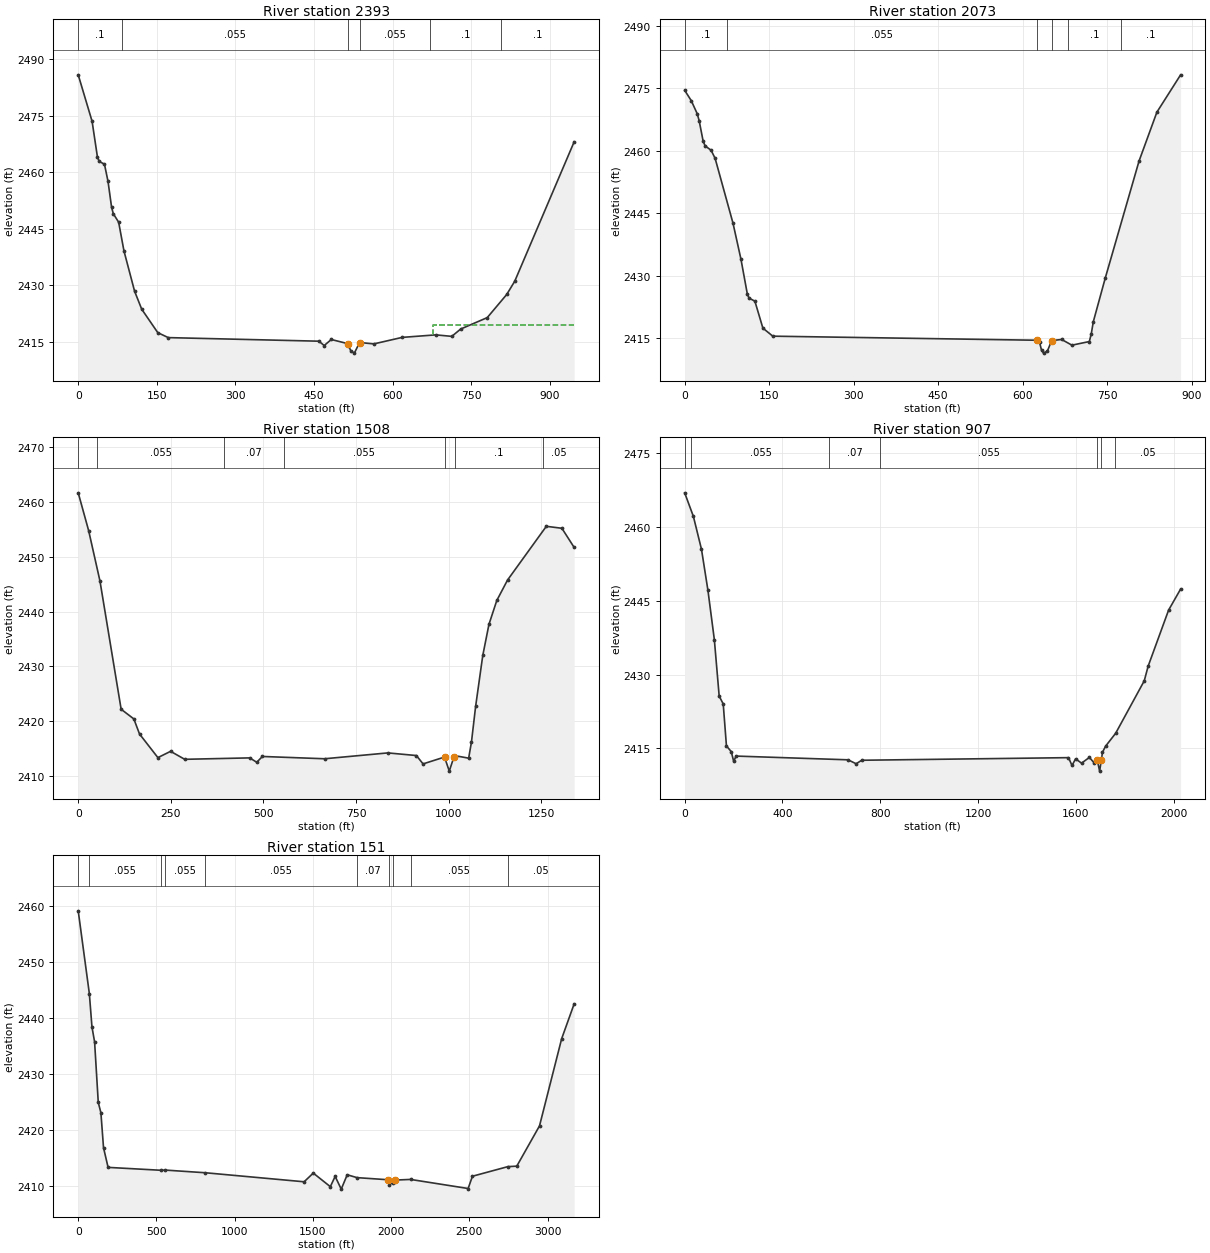
Type RM Length L Ch R = 1 ,2393    ,310.4,319.4,305.6
XS GIS Cut Line= 2
2055132.04184617323687.6558785652055362.61899882324605.883477616
#Sta/Elev= 30
       0 2485.86    26.5 2473.51    36.6 2464.12      40 2462.86    50.1 2462.13
    56.9 2457.55    63.7  2450.7      67 2448.97    77.2 2446.72    87.3 2439.11
   107.6  2428.4   121.2 2423.62   151.9 2417.39   171.9 2416.07   459.4 2415.12
   469.6 2413.97   483.1 2415.57   514.2 2414.48   520.3 2412.59   527.1 2411.95
   537.2 2414.77   564.3  2414.4   618.4 2416.13   682.7  2416.8   713.1  2416.4
   730.1 2418.35   780.8 2421.38     818 2427.53   833.3 2431.05   946.7 2468.07
#Mann= 6 ,-1 , 0
       0      .1       0   83.53    .055       0   514.2    .045       0
   537.2    .055       0  671.87      .1       0  807.81      .1       0
#XS Ineff= 2 , 0
                          676.81         2419.49
Permanent Ineff=
       F       F
Bank Sta=514.2,537.2
XS Rating Curve= 0 ,0
Exp/Cntr(USF)=0,0
Exp/Cntr=0.3,0.1

Type RM Length L Ch R = 1 ,2073    ,548.4,565.3,550.8
XS GIS Cut Line= 2
2054829.09273904323784.5632309622055155.61245893324601.942782326
#Sta/Elev= 30
       0 2474.48    11.6 2472.02    22.2 2468.88    25.7 2467.19    32.8 2462.25
    36.3 2461.15    46.9 2460.09      54 2458.16    85.8 2442.57    99.9 2433.93
   111.1 2425.66   114.1 2424.62   124.6 2423.87   138.8  2417.4   156.4 2415.47
   626.1 2414.49   629.9 2413.97   633.4 2412.07   636.9  2411.4   643.7 2411.88
   651.3  2414.4     669 2414.68   687.3 2413.31   718.2 2414.18   721.7 2416.08
   725.2 2418.92   746.4 2429.39   806.5 2457.54   838.1 2469.24   880.2  2478.2
#Mann= 6 ,-1 , 0
       0      .1       0   74.67    .055       0   626.1    .045       0
   651.3    .055       0  680.11      .1       0  774.97      .1       0
Bank Sta=626.1,651.3
XS Rating Curve= 0 ,0
Exp/Cntr(USF)=0,0
Exp/Cntr=0.3,0.1

Type RM Length L Ch R = 1 ,1508    ,603.1,600.5,592.9
XS GIS Cut Line= 2
 2054222.2982184 323689.038481492054904.88872673324840.909964308
#Sta/Elev= 30
       0 2461.71    28.2 2454.79    58.7  2445.6   115.9 2422.15   150.2 2420.38
   165.5 2417.63   215.1 2413.31   249.4 2414.46   287.5    2413     463 2413.26
     482 2412.46   497.3 2413.52   665.1  2413.1   835.9 2414.17     913 2413.69
     931 2412.16   988.9 2413.41  1001.8 2410.84  1014.7 2413.51  1015.9 2413.68
  1054.1 2413.21  1061.7 2416.17  1072.9 2422.67  1092.2 2431.98  1108.9 2437.67
  1130.1 2442.04  1159.1 2445.77  1263.8 2455.59  1305.8 2455.23  1338.9 2451.73
#Mann= 7 ,-1 , 0
       0    .055       0   51.31    .055       0  394.85     .07       0
  554.25    .055       0   988.9    .045       0  1015.9      .1       0
 1255.48     .05       0
Bank Sta=988.9,1014.7
XS Rating Curve= 0 ,0
Exp/Cntr(USF)=0,0
Exp/Cntr=0.3,0.1

Type RM Length L Ch R = 1 ,907     ,722.5,756.2,737.7
XS GIS Cut Line= 3
 2054118.0135574323641.6363628552054032.68974386324608.639582999
2054866.96703183325258.048608292
#Sta/Elev= 30
       0 2466.95    35.7 2462.14    68.7 2455.47      95 2447.16   121.4 2437.06
   141.1 2425.61   157.6 2424.04   170.8 2415.49   190.5 2414.33   200.4 2412.36
   210.3 2413.43   668.1 2412.67     701 2411.87   724.1 2412.58  1569.5 2413.11
  1583.9 2411.52  1598.6 2412.87  1622.9 2411.99    1655 2413.16  1675.3 2411.99
  1687.5 2412.57  1696.8 2410.37  1703.8  2412.6  1708.5 2414.21  1721.1 2415.44
  1762.3 2418.06  1879.3 2428.73  1895.3 2431.72  1978.8  2443.1    2028 2447.39
#Mann= 7 ,-1 , 0
       0    .055       0   27.88    .055       0  591.87     .07       0
  799.85    .055       0  1687.5    .045       0  1703.8    .055       0
 1758.82     .05       0
Bank Sta=1687.5,1703.8
XS Rating Curve= 0 ,0
Exp/Cntr(USF)=0,0
Exp/Cntr=0.3,0.1

Type RM Length L Ch R = 1 ,151     ,151,151,151
XS GIS Cut Line= 4
2054027.94953199323627.415727265 2053781.4585151324760.326362629
2054573.07389629325755.7708539542055274.62525208325988.041235263
#Sta/Elev= 30
       0 2459.06    71.1 2444.31    87.9 2438.34   104.7 2435.69   128.2 2424.87
     145 2423.05   161.8 2416.79     191 2413.29   531.1 2412.77     555 2412.81
   813.1 2412.33  1444.1 2410.72  1502.6 2412.27  1611.6 2409.85  1642.5 2411.68
  1681.4 2409.41  1719.6 2411.97  1782.6 2411.46  1981.9 2411.08  1987.2 2410.19
  2011.4 2410.55  2024.12411.022  2124.2 2411.14  2492.6 2409.52  2520.1 2411.71
    2746 2413.42  2803.6 2413.51  2948.8 2420.69  3090.5 2436.25  3170.3 2442.46
#Mann= 10 ,-1 , 0
       0    .055       0    71.1    .055       0   531.1     .07       0
     555    .055       0   813.1    .055       0  1782.6     .07       0
  1987.2    .045       0  2011.4     .07       0  2124.2    .055       0
    2746     .05       0
Bank Sta=1981.9,2024.1
XS Rating Curve= 0 ,0
Exp/Cntr(USF)=0,0
Exp/Cntr=0.3,0.1
LCMann Table=0

Chan Stop Cuts=-1
Use User Specified Reach Order=0
Composite Channel Slope=5